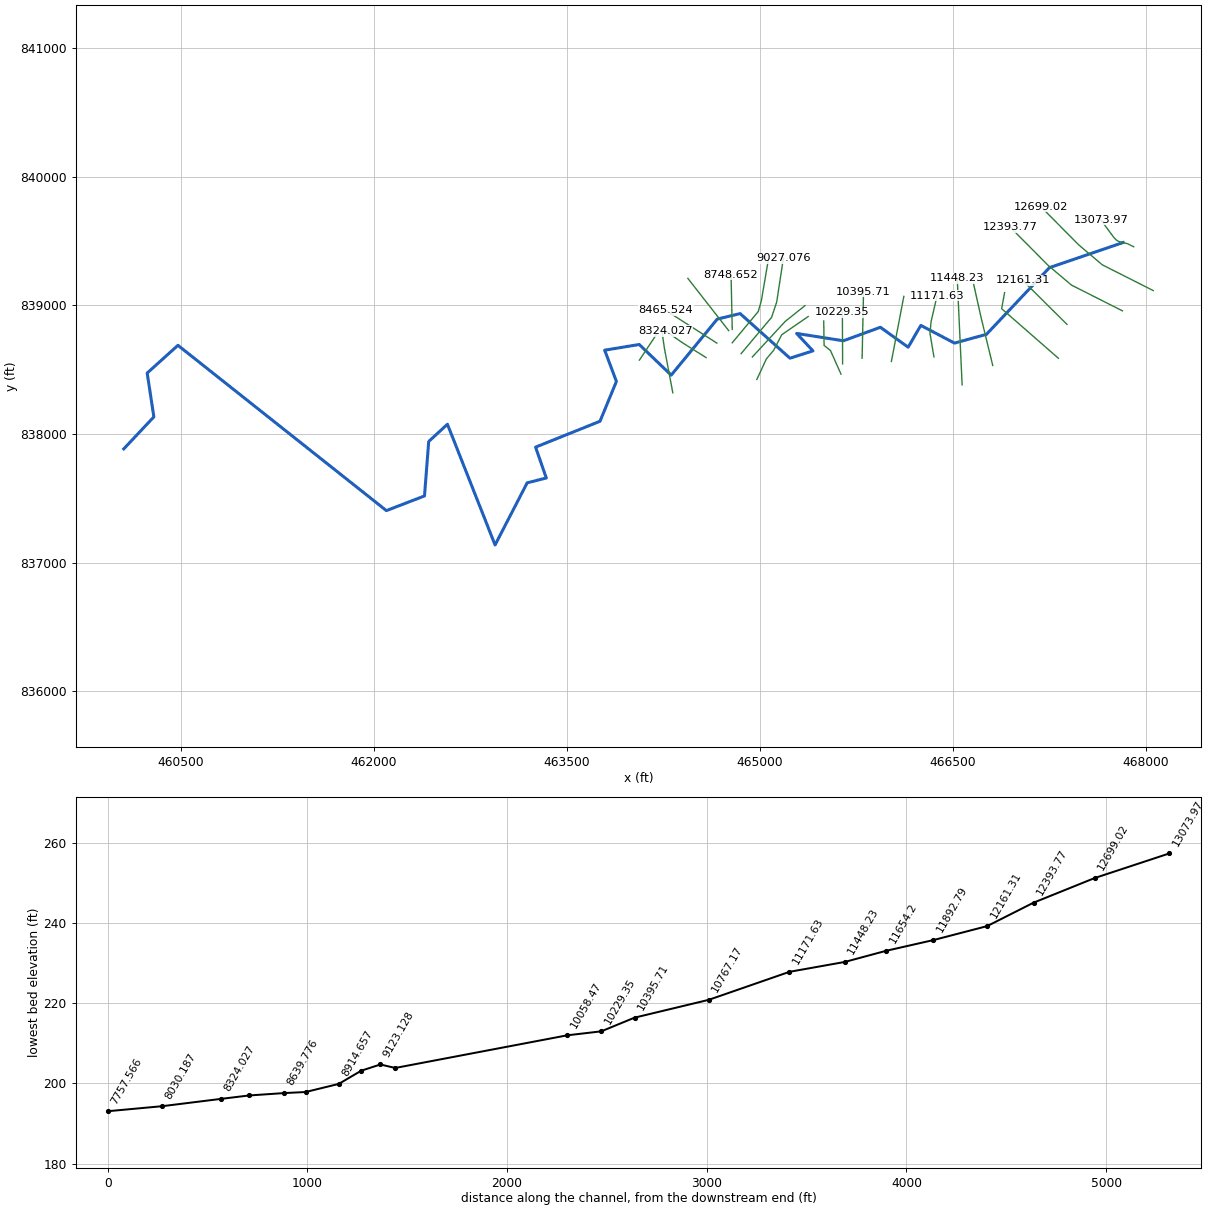
--- 7217_ras.prj (project) ---

Proj Title=7217
Current Plan=p01
Default Exp/Contr=0.3,0.1
English Units
Geom File=g01
Flow File=f01
Plan File=p01
Y Axis Title=Elevation
X Axis Title(PF)=Main Channel Distance
X Axis Title(XS)=Station
BEGIN DESCRIPTION:
RFD model 7217 exported to HEC-RAS
END DESCRIPTION:

--- 7217_ras.p01 (plan) ---

Plan Title=Plan 01
Program Version=4.10
Short Identifier=Plan 01
Geom File=g01
Flow File=f01
Subcritical Flow
Calc Critical at every XS
Secant Critical Depth

--- 7217_ras.f01 (steady flow) ---

Flow Title=Flow 01
Program Version=5.01
Number of Profiles= 6
Profile Names=10yr,25yr,50yr,100yr,100plus,500yr
River Rch & RM=7217,34,13073.97
  712.95 1078.48 1405.27 1678.71 2450.91 3268.96
River Rch & RM=7217,34,12699.02
  723.31 1094.37 1426.17 1703.86 2487.64  3311.7
River Rch & RM=7217,34,12393.77
  791.64 1198.52 1562.68 1867.53 2726.59 3585.22
River Rch & RM=7217,34,12161.31
  795.02 1203.71  1569.5 1875.74 2738.58 3598.98
River Rch & RM=7217,34,11892.79
  808.76 1224.83 1597.35  1909.3 2787.58 3655.35
River Rch & RM=7217,34, 11654.2
  812.46 1230.53 1604.86 1918.35 2800.79 3670.53
River Rch & RM=7217,34,11448.23
  838.47 1270.45 1657.43 1981.64  2893.2 3776.08
River Rch & RM=7217,34,11171.63
  843.91 1278.85 1668.53 1995.05 2912.78 3798.55
River Rch & RM=7217,34,10767.17
  855.51 1296.75 1692.18 2023.61 2954.46  3846.3
River Rch & RM=7217,34,10395.71
 1119.46 1698.72 2218.86 2654.65  3875.8 4859.41
River Rch & RM=7217,34,10229.35
 1122.87    1704 2225.84 2663.08  3888.1 4872.98
River Rch & RM=7217,34,10058.47
 1124.58 1706.63 2229.32  2667.3 3894.25 4879.76
River Rch & RM=7217,34,9197.642
 1144.98 1738.17 2271.05 2717.72 3967.88 4960.85
River Rch & RM=7217,34,9123.128
    1149 1744.41 2279.32 2727.74 3982.51 4977.01
River Rch & RM=7217,34,8914.657
 1152.35  1749.6 2286.21 2736.09 3994.69 4990.45
River Rch & RM=7217,34,8748.652
 1336.98 2033.31 2660.17 3186.44 4652.21 5698.38
River Rch & RM=7217,34,8639.776
 1340.23 2038.35 2666.85 3194.53 4664.02 5711.13
River Rch & RM=7217,34,8465.524
 1349.31 2052.44 2685.54 3217.16 4697.05 5746.78
River Rch & RM=7217,34,8324.027
 1351.26 2055.45 2689.54    3222 4704.12 5754.41
River Rch & RM=7217,34,8030.187
  1362.9 2073.52 2713.51 3251.03  4746.5 5800.09
River Rch & RM=7217,34,7757.566
 1366.45 2079.04 2720.82 3259.89 4759.43 5814.02
River Rch & RM=7217,34,7569.914
 1369.04 2083.04 2726.14 3266.32 4768.83 5824.14
River Rch & RM=7217,34,7326.451
  1374.2 2091.06 2736.77  3279.2 4787.63 5844.37
River Rch & RM=7217,34,6957.396
 1565.76 2386.41    3127 3750.03 5475.05 6569.85
River Rch & RM=7217,34,6717.807
 1571.72 2395.66 3139.27  3764.9 5496.75 6592.76
River Rch & RM=7217,34, 6384.26
 1576.72 2403.43 3149.59  3777.4    5515 6612.02
River Rch & RM=7217,34, 6255.49
 1577.66 2404.89 3151.52 3779.74 5518.42 6615.63
River Rch & RM=7217,34,5758.615
 1660.81  2533.7 3322.25 3986.31 5820.02 6931.53
River Rch & RM=7217,34,5143.096
 1666.43 2542.42  3333.8 4000.28  5840.4 6952.78
River Rch & RM=7217,34,4142.639
 1581.41 2410.72 3159.25 3789.11 5532.11 6630.06
River Rch & RM=7217,34,3560.041
 1664.25 2539.03 3329.31 3994.85 5832.48 6944.52
River Rch & RM=7217,34,3283.392
 1666.43 2542.42  3333.8 4000.28  5840.4 6952.78
Boundary for River Rch & Prof#=7217,34,1
Up Type= 0
Dn Type= 2
Boundary for River Rch & Prof#=7217,34,2
Up Type= 0
Dn Type= 2
Boundary for River Rch & Prof#=7217,34,2
Up Type= 0
Dn Type= 2
Boundary for River Rch & Prof#=7217,34,2
Up Type= 0
Dn Type= 2
Boundary for River Rch & Prof#=7217,34,2
Up Type= 0
Dn Type= 2
Boundary for River Rch & Prof#=7217,34,2
Up Type= 0
Dn Type= 2

--- 7217_ras.g01 (geometry) ---

Geom Title=7217
Program Version=4.10

River Reach=7217,34
Reach XY= 30
467824.446663827839487.520728856467251.944755375839292.290497363
466762.276524931838773.909617767466514.012636006838705.854062185
466252.207080454  838843.3540622466153.943191588838673.909617737
465937.970969349838828.770728886465650.470969349838723.909617752
465286.929302692  838780.8540622465414.012636036838645.437395558
465235.242318273838588.392053187464847.837867498838935.310080737
464670.060089767 838892.25452517464312.421200842838456.837858513
464063.810089737838695.032302961463795.060089707838650.587858513
463886.726756394838408.226747379463758.948978603 838098.50452517
463258.254534215837897.115636274463341.587867498837657.532302961
463192.976756424837620.032302916462943.510972202837136.911277831
462573.212555528838075.127813205462427.657000035 837941.23892431
462394.879222304837517.905590996 462098.76811111837404.016702101
460478.651386231838688.554003596460239.673474371838473.022880375
460291.611719728838132.393316254460057.586070091837883.672737569

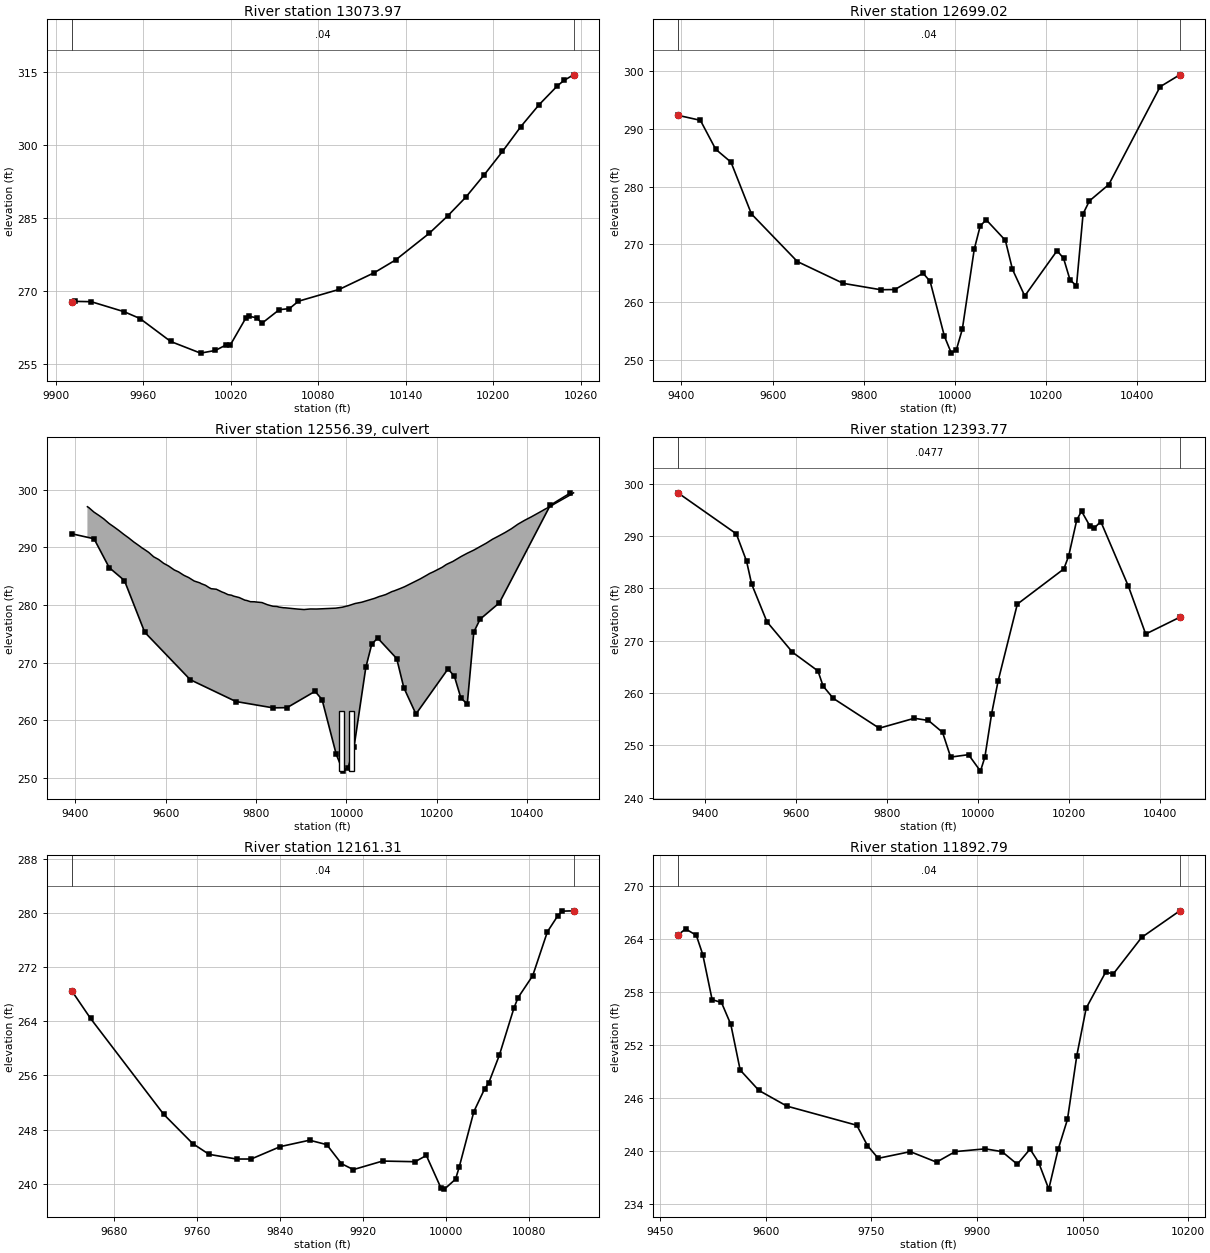
Type RM Length L Ch R = 1 ,13073.97,374.953500,374.953500,374.953500
XS GIS Cut Line= 6
467906.678774089839454.519301206  467857.6644831839478.662076548
467788.074496269839496.797889456467769.242376328839508.998804167
467750.582431197839529.167037159467651.026063204 839663.78933996
#Sta/Elev= 30
9910.969267.77939912.889267.92469924.323267.85889946.911265.80429957.744264.4153
9978.851259.70549999.314257.318610009.48257.868510016.62258.961610019.79  259.01
10030.43264.535510032.52264.8584 10037.8264.572110041.46263.445110053.38266.2342
10060.24266.434410066.48267.958310094.63270.400510118.46273.793710133.17276.4175
10156.18281.864810168.75285.398310181.32289.283910193.89293.847310206.46298.6486
10219.04  303.7410231.61308.243410244.18312.113510248.67313.209710255.23314.3543
#Mann= 3 , 0 , 0
9910.969    0.04       09910.969    0.04       010255.23    0.04       0
#XS Ineff= 2 , 0
       0                               0
Bank Sta=9910.969,10255.23
Exp/Cntr=0.3,0.1

Type RM Length L Ch R = 1 ,12699.02,305.250300,305.250300,305.250300
XS GIS Cut Line= 4
 468058.95832403839113.842672333467662.690962926839314.218829751
467480.399296254 839468.29869087467185.260407358839765.607718647
#Sta/Elev= 30
9392.253292.34519441.512291.48089475.129  286.479508.746284.23319553.569275.2708
9654.421267.02359755.273263.24339837.511262.14289868.493262.17629930.457265.0079
9945.948263.57759977.307 254.0799992.421251.165210003.49251.743810016.59255.3075
10042.78269.161510055.87273.186510068.96274.256110111.04270.6963 10126.7265.6631
10153.62261.065910224.59268.900610238.79267.597410252.98263.853710267.18262.8104
 10281.7275.296410295.56277.521810338.15280.358810450.79297.292810493.91299.3564
#Mann= 3 , 0 , 0
9392.253    0.04       09392.253    0.04       010493.91    0.04       0
#XS Ineff= 2 , 0
       09865.061         10055.2       0
Bank Sta=9392.253,10493.91
Exp/Cntr=0.3,0.1

Type RM Length L Ch R = 2 ,12556.39,,,
Bridge Culvert--1,0,-1,-1, 0
Deck Dist Width WeirC Skew NumUp NumDn MinLoCord MaxHiCord MaxSubmerge Is_Ogee
126.541,52.168,2.6,0,156,156, , , 0.95, 0, 0,0,,
 9426.87 9429.54 9430.09 9441.12 9452.15 9453.25 9463.18 9474.21 9476.96 9485.24
 9496.27 9500.66 9507.30 9518.33 9524.37 9529.36 9540.39 9548.08 9551.41 9562.44
 9571.78 9573.47 9584.50 9595.49 9595.53 9606.56 9617.59 9619.20 9628.62 9639.65
 9642.90 9650.66 9650.68 9661.96 9663.13 9675.58 9678.75 9688.02 9695.54 9700.47
 9712.34 9712.92 9725.37 9729.13 9737.81 9745.92 9750.26 9762.71 9762.71 9775.16
 9779.51 9787.61 9796.30 9800.05 9812.50 9813.09 9824.95 9829.89 9837.40 9843.80
 9846.27 9850.55 9860.67 9864.44 9875.08 9878.34 9889.48 9892.23 9903.88 9906.12
 9918.29 9920.02 9932.69 9933.91 9947.09 9947.81 9961.50 9961.70 9975.60 9975.90
 9989.49 9990.3010003.3910004.7110017.2810019.1110031.1810033.5110045.0710047.92
10058.9610062.3210072.8610076.7210086.7510091.1310100.6510105.5310114.5410119.93
10128.4410134.3410142.3310148.7410156.2310163.1410170.1210177.5510184.0210191.95
10197.9110206.3510211.8110220.7610225.7010235.1610239.5910249.5710253.4910263.97
10267.3810278.3710281.2810292.7810295.1710307.1810309.0710321.5810322.9610335.99
10336.8610350.3910350.7510364.6510364.7910377.7610378.5210379.2310392.1110394.01
10405.6910408.7810419.2810423.5510432.8610438.3310446.4510453.1010460.0310467.88
10473.6210482.6510487.2010497.4210500.7910502.33
  297.04  296.90  296.88  296.12  295.55  295.48  294.92  294.17  294.01  293.56
  292.93  292.65  292.25  291.62  291.25  290.93  290.32  289.87  289.71  289.12
  288.46  288.35  287.88  287.23  287.22  286.75  286.13  286.06  285.73  285.17
  285.04  284.76  284.76  284.19  284.15  283.83  283.69  283.41  283.03  282.82
  282.72  282.69  282.22  282.12  281.79  281.68  281.53  281.28  281.28  280.83
  280.77  280.56  280.55  280.51  280.42  280.41  280.04  279.94  279.77  279.75
  279.73  279.63  279.51  279.50  279.41  279.37  279.28  279.28  279.21  279.20
  279.28  279.30  279.28  279.29  279.33  279.33  279.39  279.39  279.44  279.44
  279.59  279.60  279.86  279.88  280.20  280.25  280.42  280.47  280.74  280.80
  281.05  281.15  281.47  281.55  281.80  281.96  282.32  282.44  282.71  282.88
  283.16  283.39  283.68  283.94  284.23  284.52  284.82  285.16  285.46  285.74
  285.98  286.34  286.54  287.01  287.20  287.54  287.75  288.21  288.40  288.84
  288.98  289.38  289.50  290.01  290.11  290.63  290.71  291.34  291.40  291.93
  291.97  292.54  292.56  293.21  293.22  293.93  293.98  294.01  294.59  294.68
  295.15  295.28  295.73  295.90  296.33  296.58  296.91  297.18  297.53  297.88
  298.12  298.54  298.74  299.19  299.37  299.45
                                                                                
                                                                                
                                                                                
                                                                                
                                                                                
                                                                                
                                                                                
                                                                                
                                                                                
                                                                                
                                                                                
                                                                                
                                                                                
                                                                                
                                                                                
                                                
 9426.87 9429.54 9430.09 9441.12 9452.15 9453.25 9463.18 9474.21 9476.96 9485.24
 9496.27 9500.66 9507.30 9518.33 9524.37 9529.36 9540.39 9548.08 9551.41 9562.44
 9571.78 9573.47 9584.50 9595.49 9595.53 9606.56 9617.59 9619.20 9628.62 9639.65
 9642.90 9650.66 9650.68 9661.96 9663.13 9675.58 9678.75 9688.02 9695.54 9700.47
 9712.34 9712.92 9725.37 9729.13 9737.81 9745.92 9750.26 9762.71 9762.71 9775.16
 9779.51 9787.61 9796.30 9800.05 9812.50 9813.09 9824.95 9829.89 9837.40 9843.80
 9846.27 9850.55 9860.67 9864.44 9875.08 9878.34 9889.48 9892.23 9903.88 9906.12
 9918.29 9920.02 9932.69 9933.91 9947.09 9947.81 9961.50 9961.70 9975.60 9975.90
 9989.49 9990.3010003.3910004.7110017.2810019.1110031.1810033.5110045.0710047.92
10058.9610062.3210072.8610076.7210086.7510091.1310100.6510105.5310114.5410119.93
10128.4410134.3410142.3310148.7410156.2310163.1410170.1210177.5510184.0210191.95
10197.9110206.3510211.8110220.7610225.7010235.1610239.5910249.5710253.4910263.97
10267.3810278.3710281.2810292.7810295.1710307.1810309.0710321.5810322.9610335.99
10336.8610350.3910350.7510364.6510364.7910377.7610378.5210379.2310392.1110394.01
10405.6910408.7810419.2810423.5510432.8610438.3310446.4510453.1010460.0310467.88
10473.6210482.6510487.2010497.4210500.7910502.33
  297.04  296.90  296.88  296.12  295.55  295.48  294.92  294.17  294.01  293.56
  292.93  292.65  292.25  291.62  291.25  290.93  290.32  289.87  289.71  289.12
  288.46  288.35  287.88  287.23  287.22  286.75  286.13  286.06  285.73  285.17
  285.04  284.76  284.76  284.19  284.15  283.83  283.69  283.41  283.03  282.82
  282.72  282.69  282.22  282.12  281.79  281.68  281.53  281.28  281.28  280.83
  280.77  280.56  280.55  280.51  280.42  280.41  280.04  279.94  279.77  279.75
  279.73  279.63  279.51  279.50  279.41  279.37  279.28  279.28  279.21  279.20
  279.28  279.30  279.28  279.29  279.33  279.33  279.39  279.39  279.44  279.44
  279.59  279.60  279.86  279.88  280.20  280.25  280.42  280.47  280.74  280.80
  281.05  281.15  281.47  281.55  281.80  281.96  282.32  282.44  282.71  282.88
  283.16  283.39  283.68  283.94  284.23  284.52  284.82  285.16  285.46  285.74
  285.98  286.34  286.54  287.01  287.20  287.54  287.75  288.21  288.40  288.84
  288.98  289.38  289.50  290.01  290.11  290.63  290.71  291.34  291.40  291.93
  291.97  292.54  292.56  293.21  293.22  293.93  293.98  294.01  294.59  294.68
  295.15  295.28  295.73  295.90  296.33  296.58  296.91  297.18  297.53  297.88
  298.12  298.54  298.74  299.19  299.37  299.45
                                                                                
                                                                                
                                                                                
                                                                                
                                                                                
                                                                                
                                                                                
                                                                                
                                                                                
                                                                                
                                                                                
                                                                                
                                                                                
                                                                                
                                                                                
                                                
BR Coef=-1 , 0 , 0 ,, 0 ,,,0.8,-1,,0,
WSPro=,,,, 1 ,,,, 0 ,,,, 0 ,,,,-1 ,-1 ,-1 , 0 , 0 , 0 , 0 , 0
Multiple Barrel Culv=2,10.499,10.499,52.168,0.13,0.4,1,8,2,251.178,243.457,2,Culvert #1, 0, 126.541
 9989.50 9989.5010010.5010010.50
Culvert Bottom n=0.13
BC Design=,, 0 ,, 0 ,,,,,,

Type RM Length L Ch R = 1 ,12393.77,232.460700,232.460700,232.460700
XS GIS Cut Line= 4
467819.374990697   838956.290589467423.107629592839156.666746418
467240.815962921839310.746607537466945.677074025839608.055635313
#Sta/Elev= 30
9341.011298.22319469.176290.38949491.588285.18379502.794280.79769536.411273.5804
 9592.44267.7614  9648.4264.18649659.674261.29819682.086258.94129782.938253.2428
9859.932 255.1419890.914254.71999921.896252.46059939.704247.72349978.985248.1862
10005.17245.040710014.84 247.72110029.74256.037910043.83262.2398 10086.1276.9551
10188.14283.672210198.82286.154310216.52293.012710227.01294.716710244.91291.9584
10255.19291.504710269.28292.736110330.08280.335510367.91271.238610442.67274.4427
#Mann= 3 , 0 , 0
9341.011  0.0477       09341.011  0.0477       010442.67  0.0477       0
#XS Ineff= 2 , 0
       09897.051        10030.37       0
Bank Sta=9341.011,10442.67
Exp/Cntr=0.3,0.1

Type RM Length L Ch R = 1 ,12161.31,268.515500,268.515500,268.515500
XS GIS Cut Line= 2
467387.899296254838851.637811244467044.149296254839192.783644557
#Sta/Elev= 30
9638.763268.51619656.936264.4278 9727.38 250.2799755.557245.92249771.302244.3384
9797.823243.64889811.912243.64949840.089245.48759868.266246.43149884.872245.7774
9899.068242.95929910.532242.0857 9938.71 243.3499970.049243.25239980.976 244.172
9995.064  239.379998.441239.198710009.15240.670810012.64242.429910026.83250.6625
10037.33254.058410041.03254.847410051.42258.993610065.51265.965510069.42267.4916
10083.62270.751410097.81 277.25110107.77279.599210112.01280.296210123.06280.3433
#Mann= 3 , 0 , 0
9638.763    0.04       09638.763    0.04       010123.06    0.04       0
#XS Ineff= 2 , 0
       09904.231                       0
Bank Sta=9638.763,10123.06
Exp/Cntr=0.3,0.1

Type RM Length L Ch R = 1 ,11892.79,238.593800,238.593800,238.593800
XS GIS Cut Line= 3
467321.545129582838587.844408438466880.572907373838973.261075124
466903.142351821839098.261075109
#Sta/Elev= 30
9475.335264.47299486.208265.15619501.404264.4401 9510.59262.26279523.871257.1588
9537.152 256.8389550.434254.35759563.715249.20149590.277 246.8939630.121245.1149
9729.338242.95299744.534240.64769759.729239.21179805.316239.9661 9842.62238.7811
9869.182239.97419911.685 240.2839935.588239.97019957.272238.54079975.432240.2568
9987.663238.726510001.99 235.72810015.28240.212210028.56243.617610041.84250.8406
10055.12256.200210083.09260.314110093.25260.0305 10133.9264.198110188.02267.2053
#Mann= 3 , 0 , 0
9475.335    0.04       09475.335    0.04       010188.02    0.04       0
#XS Ineff= 2 , 0
       09765.872        10052.86       0
Bank Sta=9475.335,10188.02
Exp/Cntr=0.3,0.1

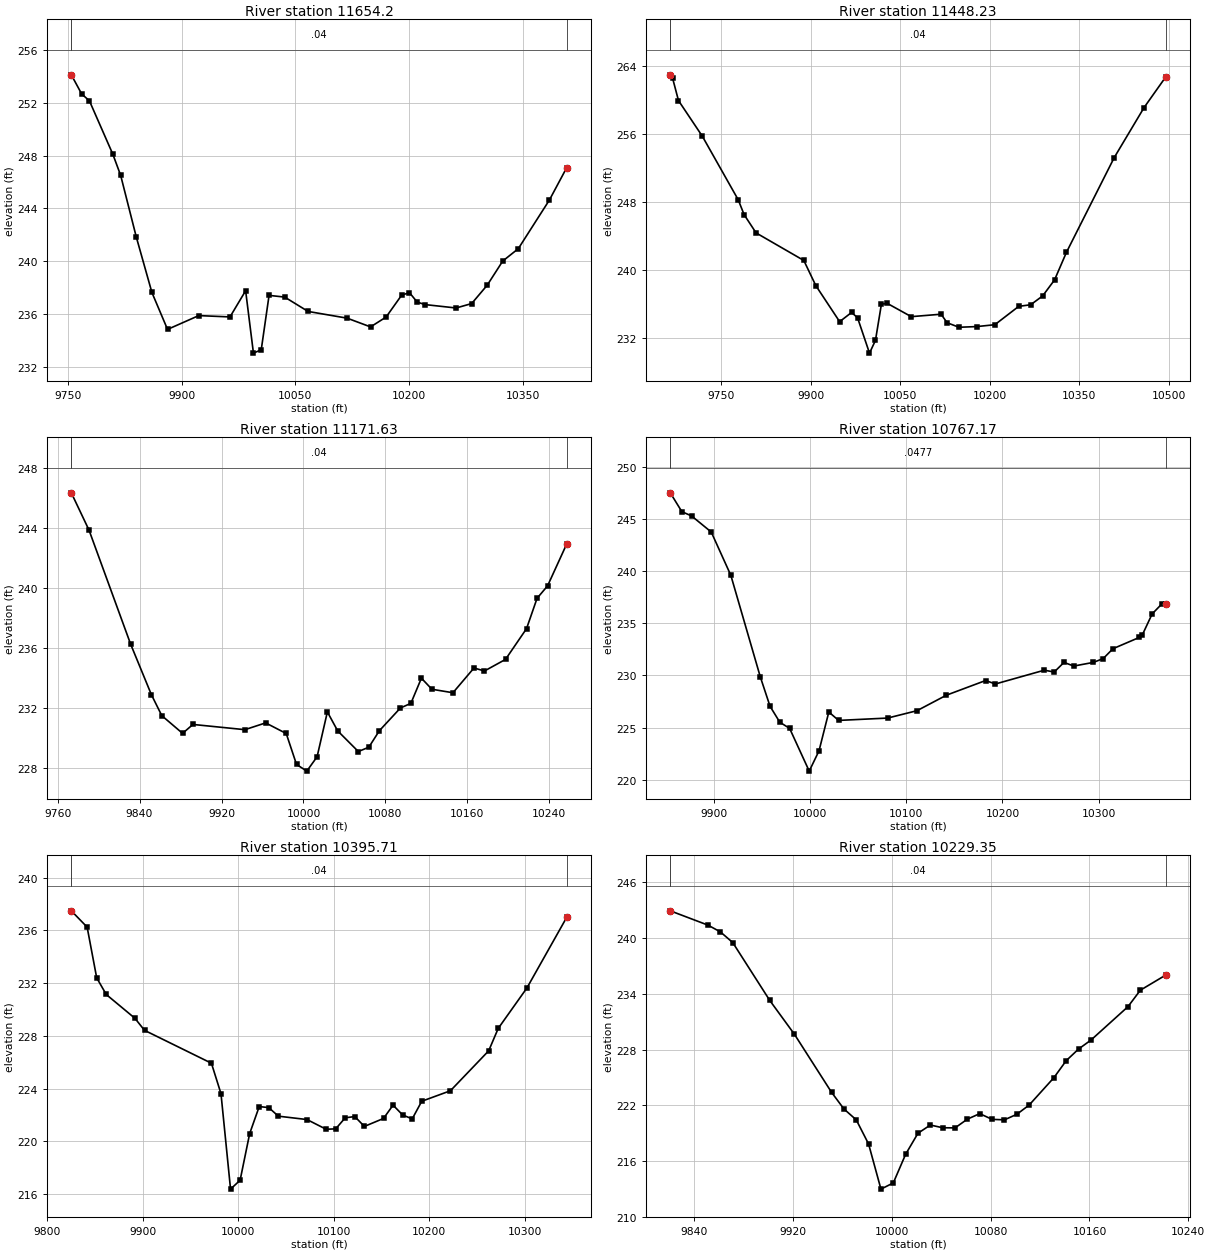
Type RM Length L Ch R = 1 , 11654.2,205.964900,205.964900,205.964900
XS GIS Cut Line= 3
466811.278812051838531.793318555 466721.00103426838903.321096331
466661.973256528839167.209985211
#Sta/Elev= 30
9754.691254.12379768.282252.67939778.573252.15039809.446248.10019819.737246.4998
9840.318241.8326  9860.9 237.6269881.482 234.8299922.646235.8752 9963.81235.7751
9984.392237.75979994.683233.030710004.97233.285310015.27237.408110035.85 237.278
10066.72236.189710118.18235.6803   10149235.018810169.49235.764810189.99 237.424
10200.23237.617510210.48 236.89910220.73236.710410261.72236.452110282.21236.7858
 10302.7238.1773 10323.2  240.0110343.69240.947310384.68244.635410407.44 247.084
#Mann= 3 , 0 , 0
9754.691    0.04       09754.691    0.04       010407.44    0.04       0
#XS Ineff= 2 , 0
       0                10100.15       0
Bank Sta=9754.691,10407.44
Exp/Cntr=0.3,0.1

Type RM Length L Ch R = 1 ,11448.23,276.599500,276.599500,276.599500
XS GIS Cut Line= 2
466573.281240702838381.247186244466535.086796269839211.108297348
#Sta/Elev= 30
9664.152262.97129667.908 262.6159677.919259.94649717.961255.75059778.025 248.298
9788.035246.53449808.057 244.3969888.141241.15489908.163238.20929948.205 233.963
9968.226235.04719978.237234.42179998.258230.266410008.27 231.76510018.28236.0352
10028.29236.102910068.33234.552910118.38234.8399 10128.4233.837510148.42233.3048
10178.45233.388210208.48 233.60610248.52235.762810268.54235.950210288.56236.9831
10308.59238.868610328.61242.122410408.69253.248710458.74259.127210494.89262.7062
#Mann= 3 , 0 , 0
9664.152    0.04       09664.152    0.04       010494.89    0.04       0
#XS Ineff= 2 , 0
       0                 10166.4       0
Bank Sta=9664.152,10494.89
Exp/Cntr=0.3,0.1

Type RM Length L Ch R = 1 ,11171.63,404.463700,404.463700,404.463700
XS GIS Cut Line= 4
466354.464575946838597.910216704466323.431589872838781.793318555
466331.678117603838871.347716704466378.336103708839073.170633376
#Sta/Elev= 30
9773.381246.31949790.712243.83149831.278236.25589851.561232.89379861.702231.5009
9881.985230.32219892.126230.91459942.833230.56649963.084231.01799983.169230.3123
9993.211228.257210003.25227.8096 10013.3228.763410023.34231.747710033.38230.4891
10053.55229.113210063.81   229.410074.07230.4948 10094.6232.006910104.86232.3184
10115.13233.991410125.39233.254510145.92233.022510166.45234.669110176.71234.4712
10197.24235.240310217.77237.288310228.03239.304610238.29 240.13110256.94242.9129
#Mann= 3 , 0 , 0
9773.381    0.04       09773.381    0.04       010256.94    0.04       0
#XS Ineff= 2 , 0
       0                10093.72       0
Bank Sta=9773.381,10256.94
Exp/Cntr=0.3,0.1

Type RM Length L Ch R = 1 ,10767.17,371.462300,371.462300,371.462300
XS GIS Cut Line= 2
466023.518395394838563.187994465466120.156240731839068.747186229
#Sta/Elev= 30
9854.833247.48299866.859245.6809 9877.04245.26459897.402243.72919917.764  239.58
9948.307229.87639958.488 227.0389968.669225.5082 9978.85224.92039999.212220.8261
10009.39222.771410019.57226.489910029.76225.683710080.66225.9082 10111.2226.6151
10141.75228.099710182.47229.503710192.65229.173510243.56230.496210253.74230.3167
10263.92231.2395 10274.1230.891510294.46231.240410304.64231.604810314.83232.5515
10342.08233.627610345.37233.882110355.55235.886810365.73236.852210369.55236.8682
#Mann= 3 , 0 , 0
9854.833  0.0477       09854.833  0.0477       010369.55  0.0477       0
#XS Ineff= 2 , 0
       0                 10224.1       0
Bank Sta=9854.833,10369.55
Exp/Cntr=0.3,0.1

Type RM Length L Ch R = 1 ,10395.71,166.362200,166.362200,166.362200
XS GIS Cut Line= 2
465796.024296284838588.443366796465807.155548155839106.590772241
#Sta/Elev= 30
 9825.45237.48989842.011236.25359852.013232.40649862.015231.14449892.022229.3389
9902.025228.42789972.041225.93269982.043223.62379992.045 216.38410002.05217.0567
10012.05220.593810022.05222.645410032.05222.566410042.06 221.91710072.06221.6602
10092.07220.924210102.07220.955710112.07221.796810122.08221.884710132.08221.1396
10152.08 221.74310162.08 222.75410172.09222.009910182.09 221.70910192.09223.0479
 10222.1223.845110262.11226.872710272.11228.574410302.12231.638910343.72236.9922
#Mann= 3 , 0 , 0
 9825.45    0.04       0 9825.45    0.04       010343.72    0.04       0
#XS Ineff= 2 , 0
       0                10141.03       0
Bank Sta=9825.45,10343.72
Exp/Cntr=0.3,0.1

Type RM Length L Ch R = 1 ,10229.35,170.874600,170.874600,170.874600
XS GIS Cut Line= 2
465644.461796269838544.441630676465642.725685135838945.483297333
#Sta/Elev= 30
9820.615242.93969851.174241.39769861.174240.67339871.174 239.5289901.174233.2905
9921.174 229.6429951.175223.40469961.175221.61389971.175220.43929981.175217.8376
9991.175212.979210001.18213.649510011.18216.736110021.18218.999610031.18219.8799
10041.18219.586210051.18219.573510061.18220.515510071.18221.105810081.18220.4878
10091.18220.440210101.18221.034310111.18222.033310131.18224.973710141.18226.8108
10151.18 228.06310161.18229.021810191.18232.624410201.18234.394410221.66236.0172
#Mann= 3 , 0 , 0
9820.615    0.04       09820.615    0.04       010221.66    0.04       0
#XS Ineff= 2 , 0
       0                               0
Bank Sta=9820.615,10221.66
Exp/Cntr=0.3,0.1

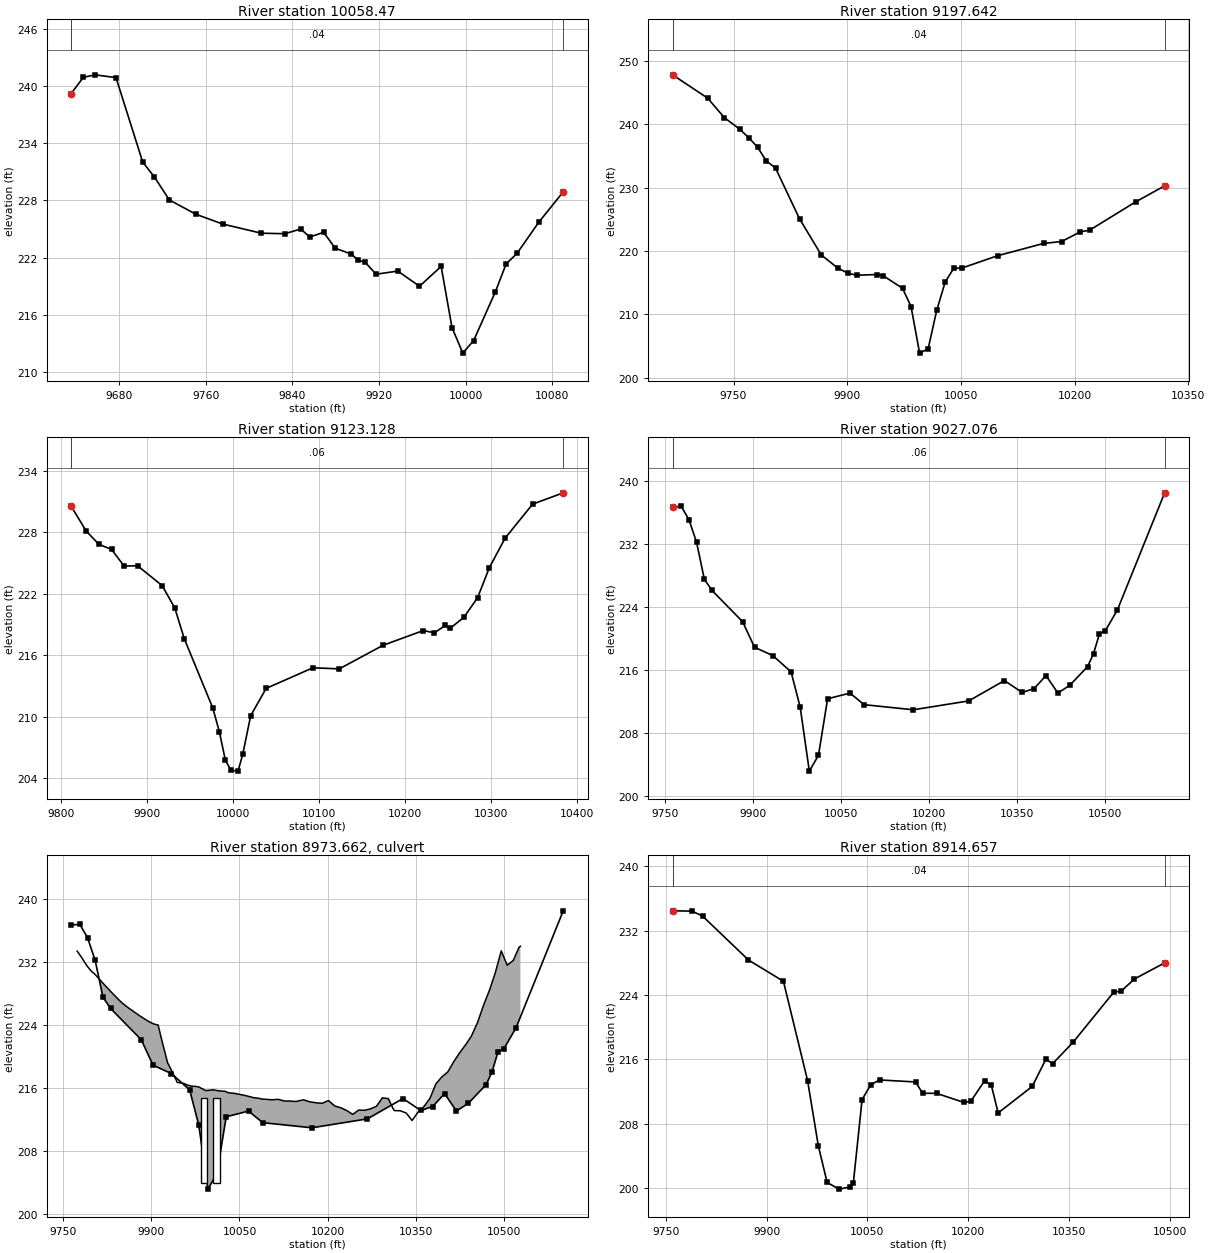
Type RM Length L Ch R = 1 ,10058.47,860.830000,860.830000,860.830000
XS GIS Cut Line= 4
465631.830103666 838464.73195233 465550.38272202838647.820532372
465500.494782387838688.052741815465497.717004629838877.636075134
#Sta/Elev= 30
9635.925239.18139647.163240.88419658.108241.14879677.333240.85379701.936232.0147
9712.832230.42919726.539228.03579751.143226.53419775.746225.51289811.336 224.554
9833.226224.49659847.749224.99649856.074224.15059868.921224.64459879.609  222.98
9894.614222.35849900.402221.7481 9907.35221.48929917.351220.25479937.353220.5843
9957.355218.99229977.357221.07189987.359214.6661 9997.36211.985510007.36213.3062
10027.36218.396610037.36221.341210047.36222.433710067.37225.688910090.01228.8863
#Mann= 3 , 0 , 0
9635.925    0.04       09635.925    0.04       010090.01    0.04       0
#XS Ineff= 2 , 0
       0                               0
Bank Sta=9635.925,10090.01
Exp/Cntr=0.3,0.1

Type RM Length L Ch R = 1 ,9197.642,74.513800,74.513800,74.513800
XS GIS Cut Line= 5
464977.663437009838423.065285623465051.831514955838582.434853092
465108.828115791838650.552741766465171.328115791838770.691630661
465376.599992633838912.146327823
#Sta/Elev= 30
9669.566247.80339715.819244.12549737.879241.04659758.056239.22679770.969237.7728
9781.756236.37659793.029234.23389805.457233.06819837.148225.05639865.869219.3461
 9887.81217.26549900.849216.48099912.618 216.158 9939.18216.2641 9947.54216.0759
9972.997 214.0929984.269211.19789995.541203.851210006.81204.536910018.09210.5881
10029.36215.106210040.63217.2482 10051.9217.309810098.34219.229110159.06221.1722
10182.92221.479610207.64223.006710219.78223.262410280.51227.730710318.88230.2691
#Mann= 3 , 0 , 0
9669.566    0.04       09669.566    0.04       010318.88    0.04       0
#XS Ineff= 2 , 0
       0                10080.87       0
Bank Sta=9669.566,10318.88
Exp/Cntr=0.3,0.1

Type RM Length L Ch R = 1 ,9123.128,96.052200,96.052200,96.052200
XS GIS Cut Line= 3
464943.072907388838598.261075124465198.281240731838874.302741811
465352.294437081838997.215772241
#Sta/Elev= 30
9811.329230.53739828.899228.11559843.629226.8259 9858.36226.32759873.091224.6994
9888.601224.73879917.283222.80419932.013220.62169943.077217.61929976.205210.8813
9983.934208.55599990.936205.76889997.553204.797110005.67204.716610011.17206.3638
 10020.4210.122810038.41212.781210092.89214.791110123.51214.6827 10174.6216.9855
10221.45218.420110234.25 218.19810247.04218.916210252.51 218.62610268.54219.7036
10284.57 221.60810298.22 224.53510316.64227.4261 10348.7230.741310384.32 231.844
#Mann= 3 , 0 , 0
9811.329    0.06       09811.329    0.06       010384.32    0.06       0
#XS Ineff= 2 , 0
       0                10102.97       0
Bank Sta=9811.329,10384.32
Exp/Cntr=0.3,0.1

Type RM Length L Ch R = 1 ,9027.076,112.419000,112.419000,112.419000
XS GIS Cut Line= 4
464855.312490717838623.608297348 465092.94269903838906.811422333
 465132.00519903839023.998922333465184.088532373  839364.7107279
#Sta/Elev= 30
9763.394236.70249778.265236.75849791.319235.07629804.373 232.1869817.426227.5414
 9830.48226.09929882.696222.13349902.925218.8852 9934.04217.83139965.155215.7654
9980.712211.28279996.269203.160910011.83205.162810027.38212.343610065.45213.0677
10089.61211.596410173.34210.947310267.74 212.07610328.44214.656610358.79213.1433
10379.02213.644110399.25  215.2910419.48213.070910439.72214.054810470.06216.4291
10480.18218.0714 10490.3220.601410500.41221.005410520.65223.588710601.28238.4878
#Mann= 3 , 0 , 0
9763.394    0.06       09763.394    0.06       010601.28    0.06       0
#XS Ineff= 2 , 0
       0                10094.69       0
Bank Sta=9763.394,10601.28
Exp/Cntr=0.3,0.1

Type RM Length L Ch R = 2 ,8973.662,,,
Bridge Culvert--1,0,-1,-1, 0
Deck Dist Width WeirC Skew NumUp NumDn MinLoCord MaxHiCord MaxSubmerge Is_Ogee
41.117,30.184,2.6,0,101,101, , , 0.95, 0, 0,0,,
 9773.65 9777.13 9782.06 9789.85 9798.24 9802.57 9814.43 9815.28 9828.00 9830.61
 9840.72 9846.79 9853.44 9862.97 9866.16 9878.88 9879.15 9891.60 9895.34 9904.32
 9911.52 9917.04 9927.70 9929.76 9942.48 9943.88 9955.20 9960.06 9967.92 9976.25
 9980.64 9992.43 9993.3610006.0810008.6110018.8010024.7910031.5110040.9710044.23
10056.9510057.1610069.6710073.3410082.3910089.5210089.7110094.2710105.0210115.77
10116.6610126.5210137.2710143.9210148.0210158.7710169.5210171.1910180.2710191.02
10198.4510201.7710211.0110212.4310222.5510232.6710242.7910246.0810252.9110263.03
10273.1510283.2710293.3910303.5110311.0710313.6310323.7510333.8710343.9910354.11
10364.2310374.3510376.0710384.4710394.6010404.7210414.8410424.9610435.0810441.07
10445.2010455.3210465.4410475.5610485.6810495.8010505.9210506.0610516.0410526.16
10528.37
  233.37  233.01  232.47  231.55  230.78  230.54  229.58  229.48  228.48  228.26
  227.49  227.03  226.60  226.05  225.90  225.22  225.21  224.61  224.44  224.12
  223.99  222.28  219.18  218.91  216.98  216.71  216.58  216.40  216.24  216.19
  216.13  215.67  215.67  215.77  215.71  215.61  215.59  215.39  215.32  215.28
  215.09  215.09  214.86  214.78  214.70  214.58  214.58  214.57  214.50  214.56
  214.54  214.35  214.34  214.29  214.31  214.50  214.25  214.23  214.12  214.06
  214.32  214.39  213.79  213.71  213.49  213.14  212.65  212.82  213.19  213.17
  213.35  213.68  214.75  214.65  213.46  213.13  213.11  212.82  211.87  212.94
  213.65  214.69  215.00  216.52  217.41  218.04  219.33  220.47  221.49  222.15
  222.63  224.30  226.47  228.38  230.65  233.40  231.58  231.60  232.17  233.87
  233.99
                                                                                
                                                                                
                                                                                
                                                                                
                                                                                
                                                                                
                                                                                
                                                                                
                                                                                
                                                                                
        
 9773.65 9777.13 9782.06 9789.85 9798.24 9802.57 9814.43 9815.28 9828.00 9830.61
 9840.72 9846.79 9853.44 9862.97 9866.16 9878.88 9879.15 9891.60 9895.34 9904.32
 9911.52 9917.04 9927.70 9929.76 9942.48 9943.88 9955.20 9960.06 9967.92 9976.25
 9980.64 9992.43 9993.3610006.0810008.6110018.8010024.7910031.5110040.9710044.23
10056.9510057.1610069.6710073.3410082.3910089.5210089.7110094.2710105.0210115.77
10116.6610126.5210137.2710143.9210148.0210158.7710169.5210171.1910180.2710191.02
10198.4510201.7710211.0110212.4310222.5510232.6710242.7910246.0810252.9110263.03
10273.1510283.2710293.3910303.5110311.0710313.6310323.7510333.8710343.9910354.11
10364.2310374.3510376.0710384.4710394.6010404.7210414.8410424.9610435.0810441.07
10445.2010455.3210465.4410475.5610485.6810495.8010505.9210506.0610516.0410526.16
10528.37
  233.37  233.01  232.47  231.55  230.78  230.54  229.58  229.48  228.48  228.26
  227.49  227.03  226.60  226.05  225.90  225.22  225.21  224.61  224.44  224.12
  223.99  222.28  219.18  218.91  216.98  216.71  216.58  216.40  216.24  216.19
  216.13  215.67  215.67  215.77  215.71  215.61  215.59  215.39  215.32  215.28
  215.09  215.09  214.86  214.78  214.70  214.58  214.58  214.57  214.50  214.56
  214.54  214.35  214.34  214.29  214.31  214.50  214.25  214.23  214.12  214.06
  214.32  214.39  213.79  213.71  213.49  213.14  212.65  212.82  213.19  213.17
  213.35  213.68  214.75  214.65  213.46  213.13  213.11  212.82  211.87  212.94
  213.65  214.69  215.00  216.52  217.41  218.04  219.33  220.47  221.49  222.15
  222.63  224.30  226.47  228.38  230.65  233.40  231.58  231.60  232.17  233.87
  233.99
                                                                                
                                                                                
                                                                                
                                                                                
                                                                                
                                                                                
                                                                                
                                                                                
                                                                                
                                                                                
        
BR Coef=-1 , 0 , 0 ,, 0 ,,,0.8,-1,,0,
WSPro=,,,, 1 ,,,, 0 ,,,, 0 ,,,,-1 ,-1 ,-1 , 0 , 0 , 0 , 0 , 0
Multiple Barrel Culv=2,10.827,10.827,30.184,0.013,0.4,1,8,2,203.95,199.55,2,Culvert #1, 0, 41.117
 9989.17 9989.1710010.8310010.83
Culvert Bottom n=0.013
BC Design=,, 0 ,, 0 ,,,,,,

Type RM Length L Ch R = 1 ,8914.657,166.005000,166.005000,166.005000
XS GIS Cut Line= 4
464786.475685135838708.200311229464988.776032373838951.299269557
465013.732629582839039.189894572465067.986101806839359.285380661
#Sta/Elev= 30
 9760.16234.44899789.119234.41129804.753233.80169873.083228.34019925.122225.6944
9961.086213.3564 9977.16205.2195 9990.17200.699610007.99199.874410023.62200.1327
 10029.2200.653110042.21211.008110055.22212.849410068.23213.439110121.85213.1871
10132.25211.784310153.04211.774110193.97210.636710204.11210.802610224.39213.3207
10234.54 212.78610244.68209.338210295.39212.634310315.68216.005310325.82215.4645
10356.25218.1244 10417.1224.382610427.25224.437410447.53225.982910492.45227.9816
#Mann= 3 , 0 , 0
 9760.16    0.04       0 9760.16    0.04       010492.45    0.04       0
#XS Ineff= 2 , 0
       0                10074.23       0
Bank Sta=9760.16,10492.45
Exp/Cntr=0.3,0.1

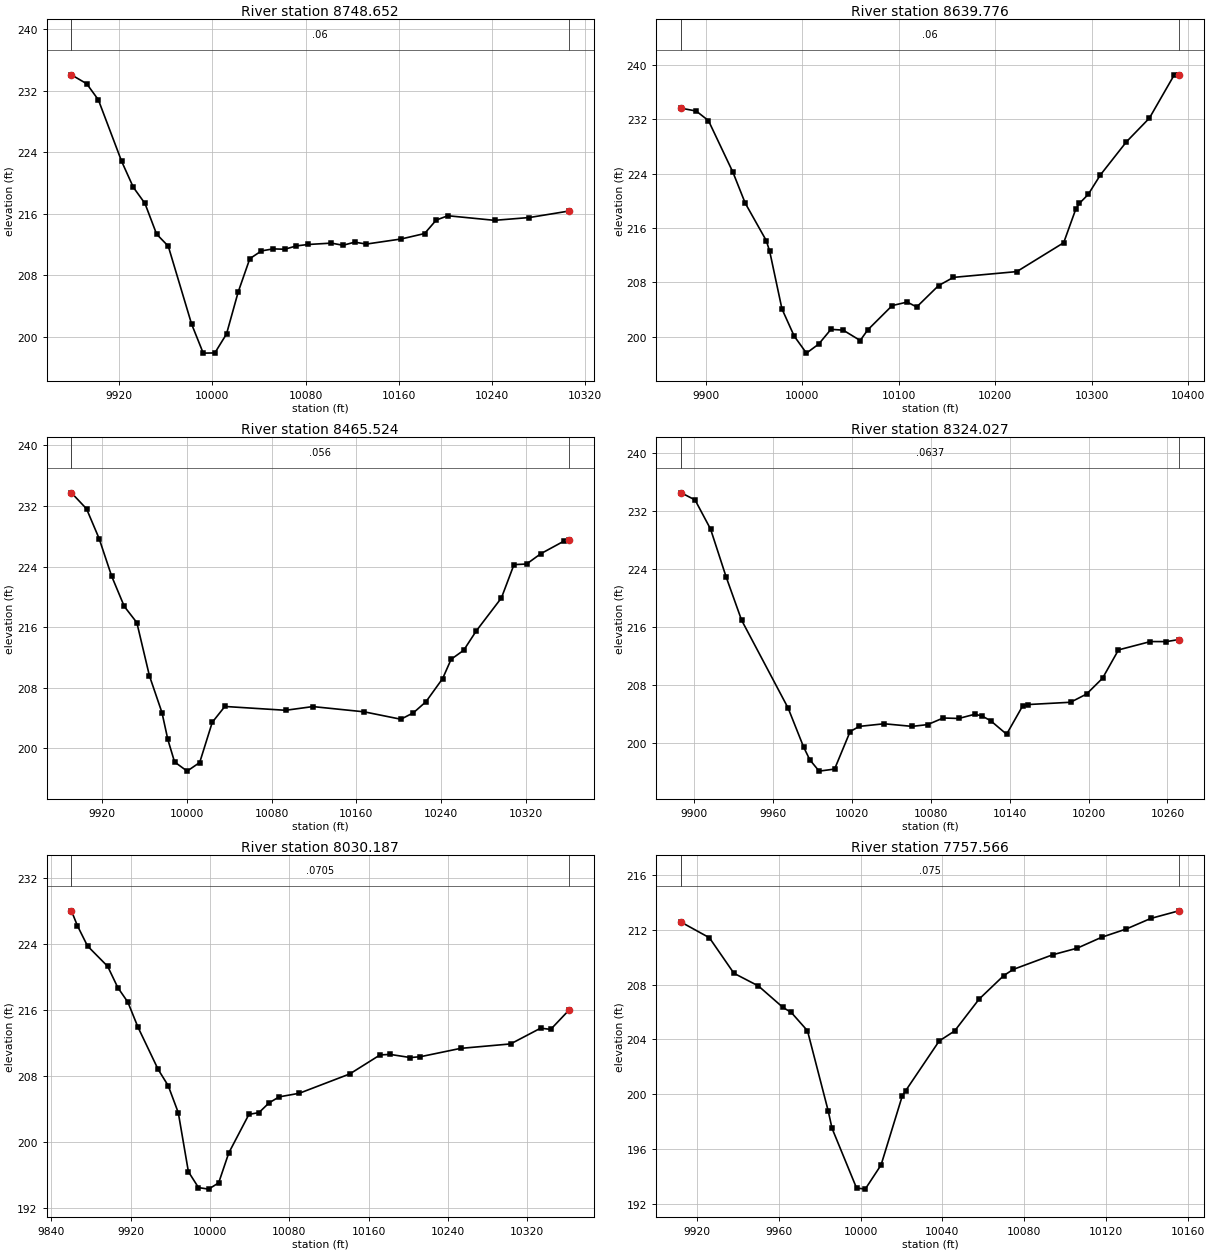
Type RM Length L Ch R = 1 ,8748.652,108.875400,108.875400,108.875400
XS GIS Cut Line= 2
464786.605893463838811.889547333464777.491310149839238.972880661
#Sta/Elev= 30
9879.006234.0492 9892.12232.88919902.122230.80219922.127222.79319932.129219.4272
9942.131 217.3249952.133213.32969962.136211.7707 9982.14201.64989992.142197.8572
10002.14 197.88210012.15200.350610022.15205.799410032.15210.143410042.15211.1509
10052.16211.413210062.16211.366410072.16 211.80310082.16 211.98510102.17212.1627
10112.17211.883910122.17212.288210132.17212.040210162.18 212.70410182.19213.4089
10192.19215.163710202.19215.7234 10242.2 215.12710272.21215.493310306.19216.3366
#Mann= 3 , 0 , 0
9879.006    0.06       09879.006    0.06       010306.19    0.06       0
#XS Ineff= 2 , 0
       0                               0
Bank Sta=9879.006,10306.19
Exp/Cntr=0.3,0.1

Type RM Length L Ch R = 1 ,8639.776,174.252400,174.252400,174.252400
XS GIS Cut Line= 2
464759.262143463838802.774964005464441.553810179839209.024964005
#Sta/Elev= 30
 9874.63233.6177 9890.15 233.2029902.845231.79289928.234 224.1869940.929219.6581
9962.713 214.1569966.319212.55849979.014204.09249991.709200.0907 10004.4197.5869
 10017.1198.917410029.79201.084510042.49200.967310060.11199.444510067.88200.9967
10093.27204.584110108.81205.098910118.66204.376910141.27207.516910156.74208.7313
10222.44209.5816   10271213.829510283.69218.832110287.37219.633310296.39220.9288
10309.08223.810710336.07228.683110359.86232.166310385.25 238.43810390.36238.5305
#Mann= 3 , 0 , 0
 9874.63    0.06       0 9874.63    0.06       010390.36    0.06       0
#XS Ineff= 2 , 0
       0                10048.94       0
Bank Sta=9874.63,10390.36
Exp/Cntr=0.3,0.1

Type RM Length L Ch R = 1 ,8465.524,141.496900,141.496900,141.496900
XS GIS Cut Line= 2
464667.031240702838705.899964005464271.197907373838959.372186244
#Sta/Elev= 30
9890.829233.74429905.116231.6306 9916.99227.70779928.865222.72759940.739218.7512
9952.614 216.6089964.488209.59169976.363204.72059981.879201.18169988.238198.2125
10000.11 196.99610011.99198.133310023.86203.442410035.74205.536110093.14205.0291
10118.86 205.51910167.32204.827210201.98203.848210213.85204.698210225.73206.1626
10241.49209.224610249.48211.766610261.35212.954510273.23215.509410296.98219.8648
10308.85224.265210320.72224.340510334.21 225.70710356.35227.390410360.86227.4658
#Mann= 3 , 0 , 0
9890.829   0.056       09890.829   0.056       010360.86   0.056       0
#XS Ineff= 2 , 0
       0                10198.91       0
Bank Sta=9890.829,10360.86
Exp/Cntr=0.3,0.1

Type RM Length L Ch R = 1 ,8324.027,293.840000,293.840000,293.840000
XS GIS Cut Line= 3
464583.914921299838593.052741796464403.793393463838705.899964049
464267.239574045838800.422533438
#Sta/Elev= 30
9890.049234.50849900.569233.52639912.369229.5092 9924.17 222.937 9935.97216.9519
9971.372204.83539983.172199.46019987.893197.69729994.973196.139710006.73196.4222
10018.57201.600210025.56202.3076 10044.4202.669710065.78202.308910077.58 202.555
10089.38203.465610101.18203.3979 10113.3203.974610118.59203.767610125.46203.0937
10137.62201.225810149.78205.112410153.73 205.31710186.27205.634510198.43206.7629
10210.59208.939910222.75 212.85410247.08214.003210259.24213.996710268.68214.2794
#Mann= 3 , 0 , 0
9890.049  0.0637       09890.049  0.0637       010268.68  0.0637       0
#XS Ineff= 2 , 0
       0                               0
Bank Sta=9890.049,10268.68
Exp/Cntr=0.3,0.1

Type RM Length L Ch R = 1 ,8030.187,272.620600,272.620600,272.620600
XS GIS Cut Line= 3
464324.842180103838319.047369465464259.479157358838665.752394572
464237.777768463 838813.32183902
#Sta/Elev= 30
9860.109228.07679866.167226.26799876.343223.81269896.695221.33899906.871218.7741
9917.047217.00039927.224213.96919947.576208.84389957.752206.86549967.928203.5857
9978.104196.43789988.281194.51049998.457194.322910008.63195.081210018.81198.7061
10039.16 203.38610049.34203.609110059.51204.789210069.69205.513410090.04205.9508
10140.92208.296410171.45210.600210181.63210.661810201.98210.281310212.16210.3822
10252.59211.392310303.13211.934110333.45213.847310343.56213.694210362.08216.0418
#Mann= 3 , 0 , 0
9860.109  0.0705       09860.109  0.0705       010362.08  0.0705       0
#XS Ineff= 2 , 0
       0                 10091.6       0
Bank Sta=9860.109,10362.08
Exp/Cntr=0.3,0.1

Type RM Length L Ch R = 1 ,7757.566,187.652700,187.652700,187.652700
XS GIS Cut Line= 2
464065.251726806838573.521491781464199.800337911838776.429477885
#Sta/Elev= 25
9912.201212.55669925.974211.42239937.973208.82869949.972   207.99961.971206.3339
9966.031205.96869973.969204.63039984.126198.76859985.968197.51239997.967193.1501
10002.22193.067210009.97194.829310020.32199.857710021.96200.242510038.41203.8828
10045.96204.615710057.96206.943610069.96 208.654 10074.6209.107210093.96210.1792
10105.96210.662610117.95211.460210129.95212.060810141.95212.832610155.67213.3873
#Mann= 3 , 0 , 0
9912.201   0.075       09912.201   0.075       010155.67   0.075       0
#XS Ineff= 2 , 0
       0                               0
Bank Sta=9912.201,10155.67
Exp/Cntr=0.3,0.1