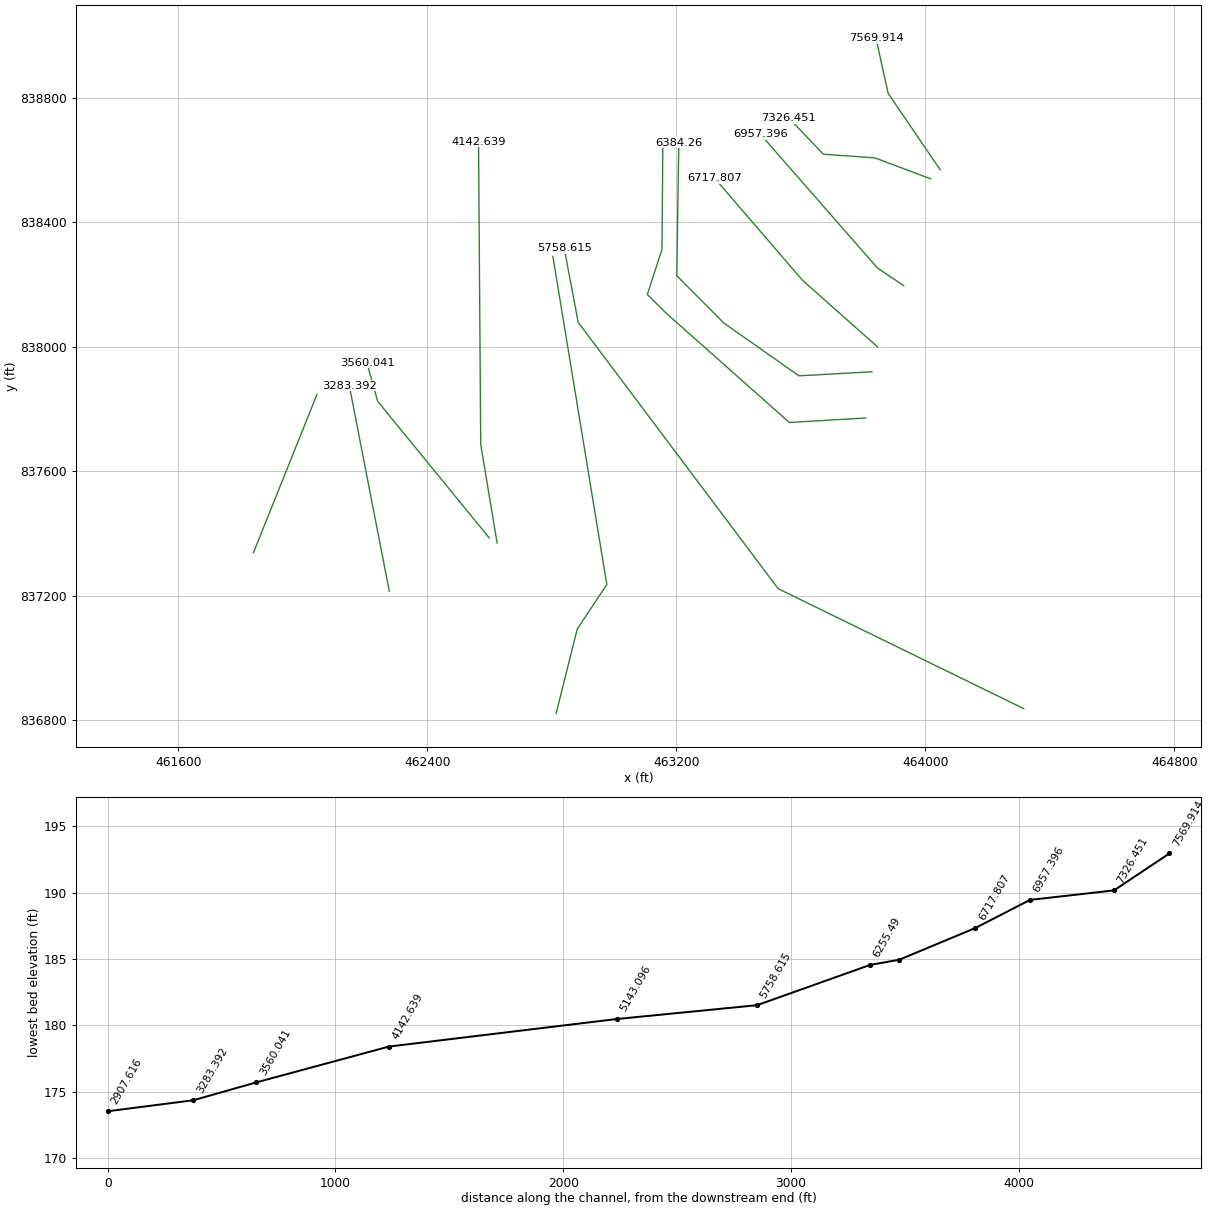
HEC-RAS study 7217_ras.prj: 7217

--- 7217_ras.g01 (geometry) --- (continued)

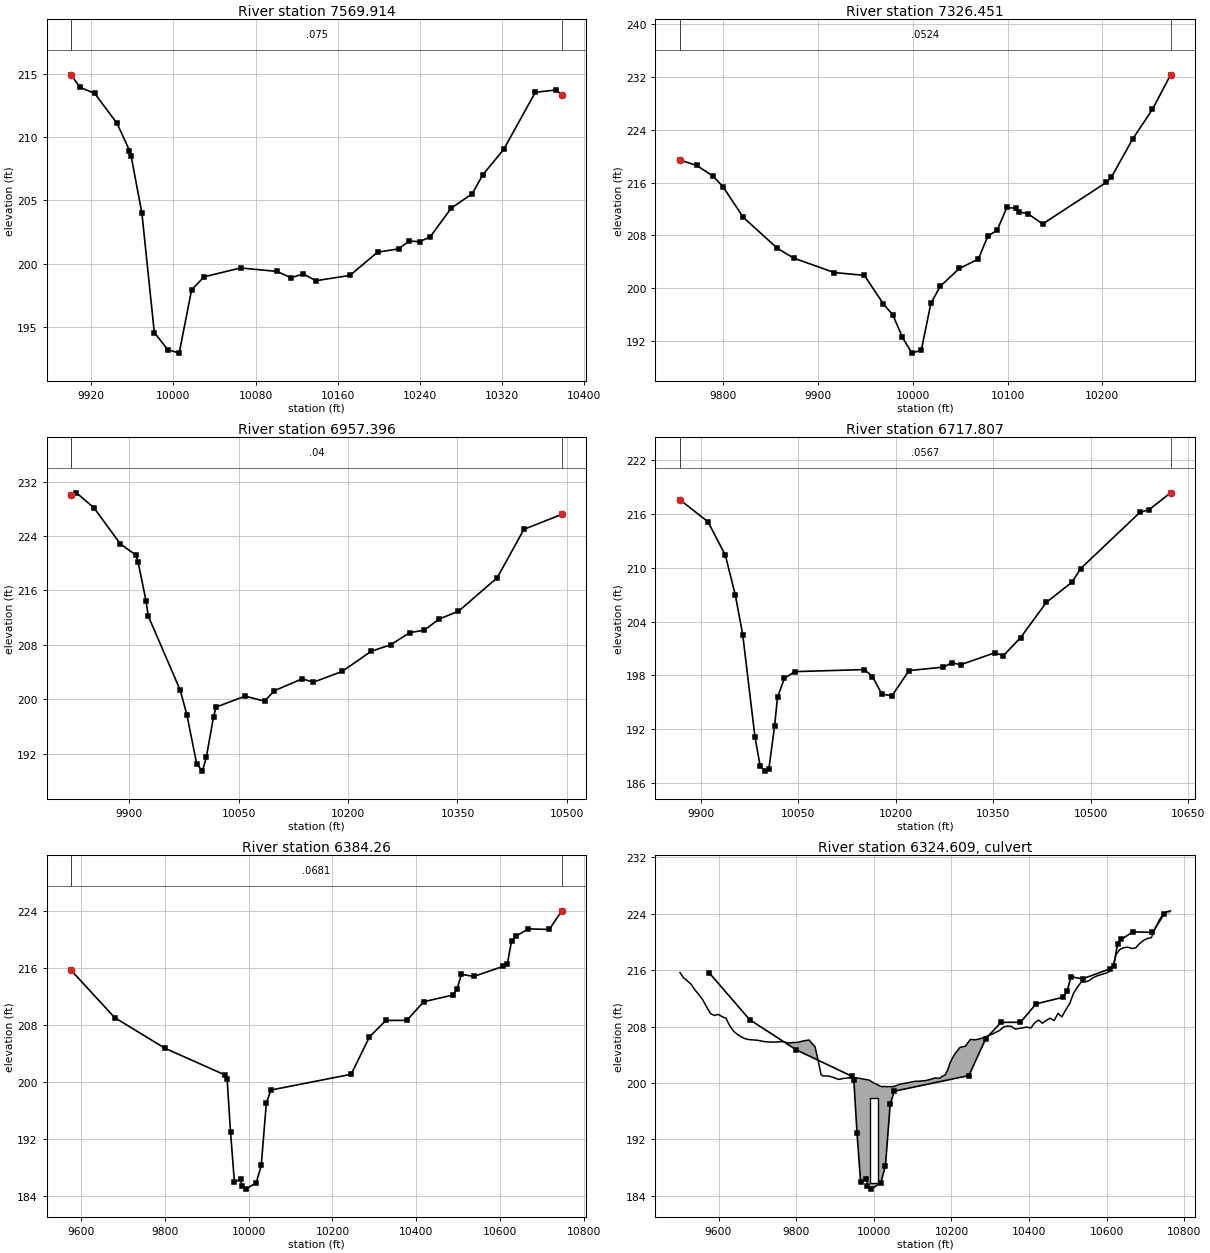
Type RM Length L Ch R = 1 ,7569.914,243.462500,243.462500,243.462500
XS GIS Cut Line= 3
464047.890615731838568.096144557463880.789921284838813.321839005
463841.727421284838990.188158453
#Sta/Elev= 30
9900.443214.89649908.798213.92429923.335213.42869945.101211.07159957.201208.9297
9958.852208.48199969.302203.98879981.403 194.5839994.369193.242610005.61192.9596
10017.71197.944110029.81198.9722 10065.4199.672410100.92   199.410114.51   198.9
10126.61199.206510138.72198.666310171.95199.085910198.91200.919910219.39201.1734
10229.63201.797910239.87201.742410250.11 202.127 10270.6204.380110291.08205.5267
10301.32207.0121 10321.8 209.03410352.52213.5176   10373213.705710378.32213.2753
#Mann= 3 , 0 , 0
9900.443   0.075       09900.443   0.075       010378.32   0.075       0
#XS Ineff= 2 , 0
       0                10121.78       0
Bank Sta=9900.443,10378.32
Exp/Cntr=0.3,0.1

Type RM Length L Ch R = 1 ,7326.451,369.055400,369.055400,369.055400
XS GIS Cut Line= 4
464017.508671254838538.799269572 463838.47221294838606.073575124
463672.456587911838618.009339005463561.779504627838734.111769572
#Sta/Elev= 30
9754.077219.41999771.706218.59899788.805 217.0079799.488215.37499820.853210.7521
9856.995206.04419874.267204.56049916.997202.37879948.817201.94939968.869 197.631
9978.895195.9475 9988.92192.58039998.946190.171110008.97190.6414   10019197.6994
10029.02200.311210049.08202.991110069.13204.413610079.15207.870610089.18208.8256
 10099.2212.230610109.23212.097210111.78211.550510121.44211.301310137.08209.7406
10204.33216.032710209.54216.782710231.96222.557710253.02227.105110272.18232.3269
#Mann= 3 , 0 , 0
9754.077  0.0524       09754.077  0.0524       010272.18  0.0524       0
#XS Ineff= 2 , 0
       09925.727        10026.02       0
Bank Sta=9754.077,10272.18
Exp/Cntr=0.3,0.1

Type RM Length L Ch R = 1 ,6957.396,239.589200,239.589200,239.589200
XS GIS Cut Line= 3
463930.920129594838195.483297343463845.850685146838252.774964015
463470.850685131838681.594408462
#Sta/Elev= 30
9820.765230.05649827.903230.34489852.015228.13729888.184222.82669909.409221.1967
9912.297220.22089923.328214.46679926.284212.26049970.193201.33639979.421197.6565
9992.705190.529110000.57189.452810005.99191.540610015.77197.422310019.27198.8608
10059.13200.4747 10085.7199.733110098.98201.257110137.29203.021710152.48 202.515
10191.97204.101910231.82207.063610258.39208.011310284.96209.819110304.39210.1461
10324.81 211.79810351.38212.940610404.52217.875610441.11224.988810492.99227.1734
#Mann= 3 , 0 , 0
9820.765    0.04       09820.765    0.04       010492.99    0.04       0
#XS Ineff= 2 , 0
       0                10061.46       0
Bank Sta=9820.765,10492.99
Exp/Cntr=0.3,0.1

Type RM Length L Ch R = 1 ,6717.807,333.546600,333.546600,333.546600
XS GIS Cut Line= 3
463847.152768463837998.434686229463605.182282358838213.278436244
463324.149296284838539.884339005
#Sta/Elev= 30
9868.438217.58469911.436215.14019938.181211.42149953.633206.92559964.927202.5578
9983.756 191.1379991.673187.94049998.818187.336410005.05187.539610013.88192.3313
10018.42195.558910028.94197.677310045.16198.431110152.15198.659210164.49197.8668
10178.89195.931710194.29195.726710220.68198.546610273.45198.932110286.64199.4207
10299.83199.1939 10352.6200.5302 10365.8200.208610392.18202.217610431.76206.1463
10471.34208.404710484.53209.9129 10575.6216.180610590.07216.5002 10622.9218.3644
#Mann= 3 , 0 , 0
9868.438  0.0567       09868.438  0.0567       0 10622.9  0.0567       0
#XS Ineff= 2 , 0
       0                10215.24       0
Bank Sta=9868.438,10622.9
Exp/Cntr=0.3,0.1

Type RM Length L Ch R = 1 , 6384.26,128.769500,128.769500,128.769500
XS GIS Cut Line= 5
463828.619782373837918.877394557463594.244782358837905.856561229
463353.359365717838075.127394557463201.701379582838227.505866781
463208.211796254  838655.0232279
#Sta/Elev= 30
9576.129215.61459679.909208.99679800.094204.70139944.385200.93159948.519200.3653
9956.607192.96469965.912185.96429981.051186.33719983.305185.42689993.273184.9476
10018.09185.842110029.94 188.27210042.16 196.98710052.88198.837910244.71201.0505
10288.51206.298210327.76208.600810377.76208.611310417.77211.216910487.78212.1682
10497.78212.980710507.78215.065610537.78214.774210607.79216.179110617.79216.5679
10627.79219.7399 10637.8220.3966 10667.8221.4393 10717.8221.357910747.83223.9697
#Mann= 3 , 0 , 0
9576.129  0.0681       09576.129  0.0681       010747.83  0.0681       0
#XS Ineff= 2 , 0
       09890.392        10077.13       0
Bank Sta=9576.129,10747.83
Exp/Cntr=0.3,0.1

Type RM Length L Ch R = 2 ,6324.609,,,
Bridge Culvert--1,0,-1,-1, 0
Deck Dist Width WeirC Skew NumUp NumDn MinLoCord MaxHiCord MaxSubmerge Is_Ogee
37.482,53.805,2.6,0,153,153, , , 0.95, 0, 0,0,,
 9500.63 9509.03 9519.05 9529.06 9539.08 9549.09 9557.30 9559.11 9569.12 9579.14
 9589.15 9599.17 9609.18 9619.20 9629.21 9639.23 9649.24 9659.26 9669.27 9679.29
 9689.30 9699.32 9709.33 9719.35 9729.36 9739.38 9739.81 9752.31 9755.32 9765.38
 9770.86 9778.44 9786.40 9791.51 9801.94 9804.57 9817.48 9817.64 9830.70 9833.02
 9843.77 9848.56 9856.83 9864.10 9869.90 9879.64 9882.96 9895.18 9896.02 9909.09
 9910.72 9922.15 9926.26 9935.22 9941.80 9948.28 9957.34 9961.35 9972.88 9974.41
 9987.48 9988.4210000.5410003.9610013.6110019.5010026.6710035.0410039.7310050.58
10052.8010065.8610066.1110078.9310081.6510091.9910097.1910105.0610112.7310118.12
10128.2710131.1910143.8110144.2510157.3210159.3510170.3810174.8910183.4510190.43
10196.5110205.9710209.5710221.5110222.6410235.7010237.0510248.7710252.5910261.83
10268.1310274.9010283.6710285.4610294.3110304.3210314.3210324.3310334.3310344.34
10354.3510364.3510374.3610384.3610394.3710404.3810414.3810424.3910434.3910444.40
10454.4010464.4110474.4210484.4210494.4310504.4310514.4410522.1910524.4510534.45
10544.4610554.4610564.4710574.4710584.4810594.4910604.4910614.5010624.5010634.51
10644.5210654.5210664.5310674.5310684.5410694.5410704.5510714.5610724.5610734.57
10744.5710754.5810764.46
  215.67  214.97  214.51  214.02  213.21  212.54  211.95  211.81  210.80  209.86
  209.57  209.73  209.41  209.18  208.08  207.31  206.87  206.52  206.27  206.15
  206.11  206.07  205.97  205.86  205.82  205.79  205.79  205.83  205.84  205.87
  205.81  205.70  205.69  205.75  205.75  205.77  205.96  205.96  206.08  206.10
  205.42  205.15  203.12  201.16  200.99  200.99  201.00  200.81  200.79  200.51
  200.52  200.65  200.67  200.73  200.81  200.74  200.72  200.68  200.58  200.55
  200.41  200.40  199.96  199.91  199.65  199.48  199.51  199.47  199.49  199.48
  199.52  199.80  199.81  199.96  199.97  200.08  200.12  200.23  200.25  200.26
  200.33  200.32  200.47  200.48  200.72  200.71  200.68  200.91  201.13  201.86
  202.90  203.87  204.18  205.02  205.06  205.22  205.33  206.18  206.17  206.12
  206.21  206.31  206.43  206.48  206.70  206.92  207.19  207.47  207.95  208.08
  208.03  207.64  207.74  207.82  207.94  207.79  208.54  208.92  208.48  208.88
  209.20  208.84  209.87  209.39  210.38  211.25  212.73  213.42  213.60  214.33
  214.32  214.52  214.92  215.18  215.36  215.52  215.73  216.32  218.28  218.97
  219.20  219.26  219.08  219.16  219.79  220.21  220.50  220.60  221.86  223.00
  223.95  224.30  224.42
                                                                                
                                                                                
                                                                                
                                                                                
                                                                                
                                                                                
                                                                                
                                                                                
                                                                                
                                                                                
                                                                                
                                                                                
                                                                                
                                                                                
                                                                                
                        
 9500.63 9509.03 9519.05 9529.06 9539.08 9549.09 9557.30 9559.11 9569.12 9579.14
 9589.15 9599.17 9609.18 9619.20 9629.21 9639.23 9649.24 9659.26 9669.27 9679.29
 9689.30 9699.32 9709.33 9719.35 9729.36 9739.38 9739.81 9752.31 9755.32 9765.38
 9770.86 9778.44 9786.40 9791.51 9801.94 9804.57 9817.48 9817.64 9830.70 9833.02
 9843.77 9848.56 9856.83 9864.10 9869.90 9879.64 9882.96 9895.18 9896.02 9909.09
 9910.72 9922.15 9926.26 9935.22 9941.80 9948.28 9957.34 9961.35 9972.88 9974.41
 9987.48 9988.4210000.5410003.9610013.6110019.5010026.6710035.0410039.7310050.58
10052.8010065.8610066.1110078.9310081.6510091.9910097.1910105.0610112.7310118.12
10128.2710131.1910143.8110144.2510157.3210159.3510170.3810174.8910183.4510190.43
10196.5110205.9710209.5710221.5110222.6410235.7010237.0510248.7710252.5910261.83
10268.1310274.9010283.6710285.4610294.3110304.3210314.3210324.3310334.3310344.34
10354.3510364.3510374.3610384.3610394.3710404.3810414.3810424.3910434.3910444.40
10454.4010464.4110474.4210484.4210494.4310504.4310514.4410522.1910524.4510534.45
10544.4610554.4610564.4710574.4710584.4810594.4910604.4910614.5010624.5010634.51
10644.5210654.5210664.5310674.5310684.5410694.5410704.5510714.5610724.5610734.57
10744.5710754.5810764.46
  215.67  214.97  214.51  214.02  213.21  212.54  211.95  211.81  210.80  209.86
  209.57  209.73  209.41  209.18  208.08  207.31  206.87  206.52  206.27  206.15
  206.11  206.07  205.97  205.86  205.82  205.79  205.79  205.83  205.84  205.87
  205.81  205.70  205.69  205.75  205.75  205.77  205.96  205.96  206.08  206.10
  205.42  205.15  203.12  201.16  200.99  200.99  201.00  200.81  200.79  200.51
  200.52  200.65  200.67  200.73  200.81  200.74  200.72  200.68  200.58  200.55
  200.41  200.40  199.96  199.91  199.65  199.48  199.51  199.47  199.49  199.48
  199.52  199.80  199.81  199.96  199.97  200.08  200.12  200.23  200.25  200.26
  200.33  200.32  200.47  200.48  200.72  200.71  200.68  200.91  201.13  201.86
  202.90  203.87  204.18  205.02  205.06  205.22  205.33  206.18  206.17  206.12
  206.21  206.31  206.43  206.48  206.70  206.92  207.19  207.47  207.95  208.08
  208.03  207.64  207.74  207.82  207.94  207.79  208.54  208.92  208.48  208.88
  209.20  208.84  209.87  209.39  210.38  211.25  212.73  213.42  213.60  214.33
  214.32  214.52  214.92  215.18  215.36  215.52  215.73  216.32  218.28  218.97
  219.20  219.26  219.08  219.16  219.79  220.21  220.50  220.60  221.86  223.00
  223.95  224.30  224.42
                                                                                
                                                                                
                                                                                
                                                                                
                                                                                
                                                                                
                                                                                
                                                                                
                                                                                
                                                                                
                                                                                
                                                                                
                                                                                
                                                                                
                                                                                
                        
BR Coef=-1 , 0 , 0 ,, 0 ,,,0.8,-1,,0,
WSPro=,,,, 1 ,,,, 0 ,,,, 0 ,,,,-1 ,-1 ,-1 , 0 , 0 , 0 , 0 , 0
Culvert=2,12,20.341,53.805,0.013,0.4,1,8,2,185.87,10000,184.67,10000,Culvert #1, 0, 37.482
Culvert Bottom n=0.013
BC Design=,, 0 ,, 0 ,,,,,,

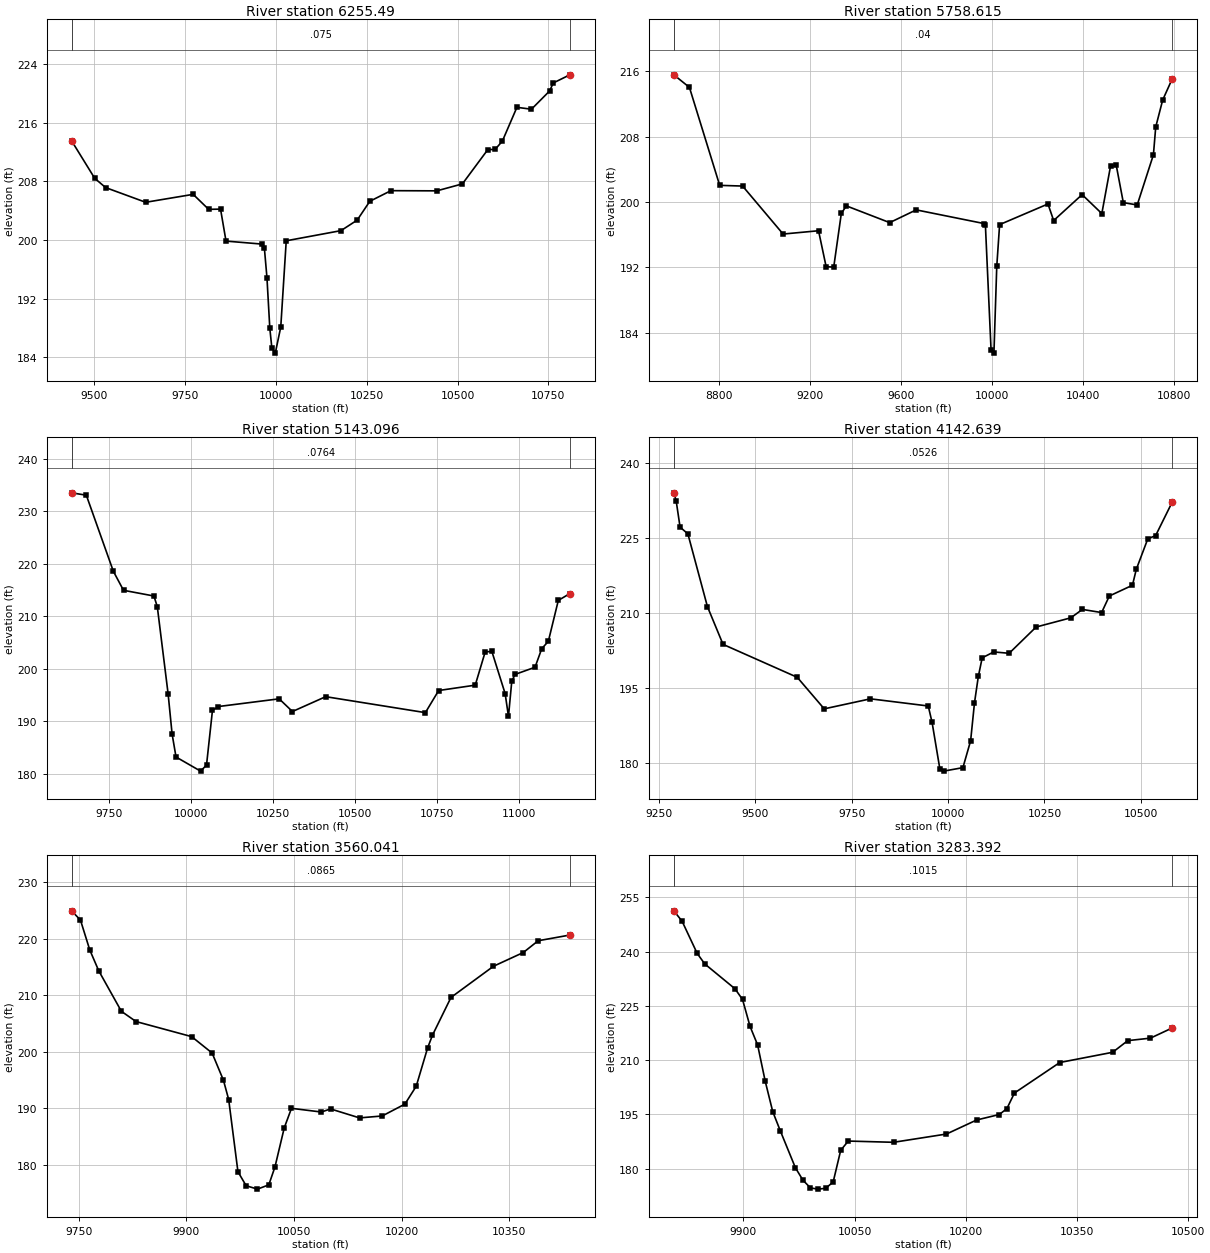
Type RM Length L Ch R = 1 , 6255.49,496.875700,496.875700,496.875700
XS GIS Cut Line= 6
463808.567699045837770.439894572463563.255199045837756.030172333
463167.421865702838107.419061244 463107.00519903838167.141283438
463154.227421254838312.280172333463157.005199045838670.613505661
#Sta/Elev= 30
9437.875213.55699501.552208.43219531.604207.16369641.794205.15649772.437206.2402
9814.995204.19379847.753 204.2239862.816199.85479962.085 199.4459968.257198.9659
9975.457194.8563 9983.32187.93919988.828185.31379998.383184.550110013.45188.1177
10028.51199.897210179.14201.283510223.69 202.719 10258.5205.292810316.64206.7443
10442.83206.719210513.21207.668910583.21212.356110603.21212.375810623.22213.5179
10663.22218.130410703.22 217.86910753.22 220.36310763.22221.456710808.83222.5684
#Mann= 3 , 0 , 0
9437.875   0.075       09437.875   0.075       010808.83   0.075       0
#XS Ineff= 2 , 0
       09851.895        10046.85       0
Bank Sta=9437.875,10808.83
Exp/Cntr=0.3,0.1

Type RM Length L Ch R = 1 ,5758.615,615.518500,615.518500,615.518500
XS GIS Cut Line= 4
464316.607660413836836.532395512463527.545160413837221.949062183
          462885838077.622903585462840.045160413838315.699062183
#Sta/Elev= 30
 8600.57215.55588669.134214.0192 8802.14202.03448902.846201.95019080.913196.0787
9236.721196.48319270.108192.08719303.496192.03329336.883 198.6019359.142199.5242
9549.583197.47689666.158199.03569965.922197.35299970.261197.20179995.272181.8641
10007.78 181.51310020.28192.135210032.79197.231710245.38199.759610270.39197.7316
10395.45200.902610482.18198.583810520.51204.397810545.52204.496910576.66199.9272
10637.72199.635310708.95205.776210719.13 209.17410749.66212.471310791.08215.0274
#Mann= 3 , 0 , 0
 8600.57    0.04       0 8600.57    0.04       010791.08    0.04       0
#XS Ineff= 2 , 0
       09819.555        10134.61       0
Bank Sta=8600.57,10791.08
Exp/Cntr=0.3,0.1

Type RM Length L Ch R = 1 ,5143.096,1000.457500,1000.457500,1000.457500
XS GIS Cut Line= 4
462814.123254597836821.394755676 462881.83158794 837092.22808902
462976.883671284837235.457255676462803.586827129838289.657395527
#Sta/Elev= 30
9634.737233.48589679.684233.03389762.045218.5484 9793.07214.9189 9885.84213.8302
9896.147211.79339929.234195.13519941.236187.55499953.238183.163410028.14180.4724
10046.23181.621810064.31192.0297 10082.4192.776110267.76194.245710308.29191.8273
10409.64194.654510713.66191.6149 10754.2195.827910865.68196.848910896.08203.1917
10916.35 203.27610956.88195.238210967.02190.899210977.15197.621710987.29198.8994
11048.09200.264211068.36203.781611088.63 205.20511119.03 212.99311154.15214.2942
#Mann= 3 , 0 , 0
9634.737  0.0764       09634.737  0.0764       011154.15  0.0764       0
#XS Ineff= 2 , 0
       0                10440.21       0
Bank Sta=9634.737,11154.15
Exp/Cntr=0.3,0.1

Type RM Length L Ch R = 1 ,4142.639,582.597400,582.597400,582.597400
XS GIS Cut Line= 3
462624.339297593837369.037396595462571.741977453837685.668582067
462564.797533035838657.890804306
#Sta/Elev= 30
9288.118234.08929294.162232.48019304.299 227.2299324.573225.87619375.259211.3245
9415.807203.7627 9608.41197.17139678.421190.85789798.424192.86279948.428191.4306
9958.428 188.1349978.429178.89539988.429 178.39510038.43179.094210058.43184.4722
10068.43192.053610078.43197.348810088.43201.067810118.43 202.24910158.43201.9769
10228.44 207.23410318.44209.074210348.44 210.75510398.44210.129110418.44213.4418
10478.44215.594810488.44218.783510518.44224.917110538.44225.502510581.34232.1856
#Mann= 3 , 0 , 0
9288.118  0.0526       09288.118  0.0526       010581.34  0.0526       0
#XS Ineff= 2 , 0
       09596.832        10109.87       0
Bank Sta=9288.118,10581.34
Exp/Cntr=0.3,0.1

Type RM Length L Ch R = 1 ,3560.041,276.649900,276.649900,276.649900
XS GIS Cut Line= 3
462598.912116319837385.408165395462240.839199662837823.776220962
462206.116977453837947.474137634
#Sta/Elev= 30
9740.114224.91129752.499223.27879765.411218.01279777.913214.32069809.528207.1413
9829.971205.32869907.444202.66639935.988199.76469951.796194.94859959.092191.5436
9972.004178.77239983.411176.29689999.218175.693810015.03176.449410023.65179.6391
10036.56 186.53710046.64189.983910088.21189.330710101.12189.877310141.49188.2908
 10173.1188.631710204.72190.729410220.52193.895710236.33 200.64610243.16202.9189
10268.98209.597910328.18215.107810369.73217.5359 10390.5219.619310434.62220.6291
#Mann= 3 , 0 , 0
9740.114  0.0865       09740.114  0.0865       010434.62  0.0865       0
#XS Ineff= 2 , 0
       0 9914.39        10109.09       0
Bank Sta=9740.114,10434.62
Exp/Cntr=0.3,0.1

Type RM Length L Ch R = 1 ,3283.392,375.775900,375.775900,375.775900
XS GIS Cut Line= 2
462277.985130936837214.089479923462149.693366319837873.689415395
#Sta/Elev= 30
9806.303251.29399817.418  248.429837.792239.5206 9847.98236.61569888.729229.7493
9898.917226.79369909.104  219.339919.291214.21389929.479204.22699939.666195.7788
9949.854 190.4819970.228180.26049980.416176.81869990.603174.675510000.79174.3458
10010.98174.570410021.17176.317110031.35185.084910041.54187.636410102.66187.2939
10173.98  189.5810214.73193.467110245.29194.977410255.48196.615610265.66200.9215
10326.79209.3548 10398.1212.181910418.47215.404110449.04216.091710478.26218.8915
#Mann= 3 , 0 , 0
9806.303  0.1015       09806.303  0.1015       010478.26  0.1015       0
#XS Ineff= 2 , 0
       0                10055.04       0
Bank Sta=9806.303,10478.26
Exp/Cntr=0.3,0.1

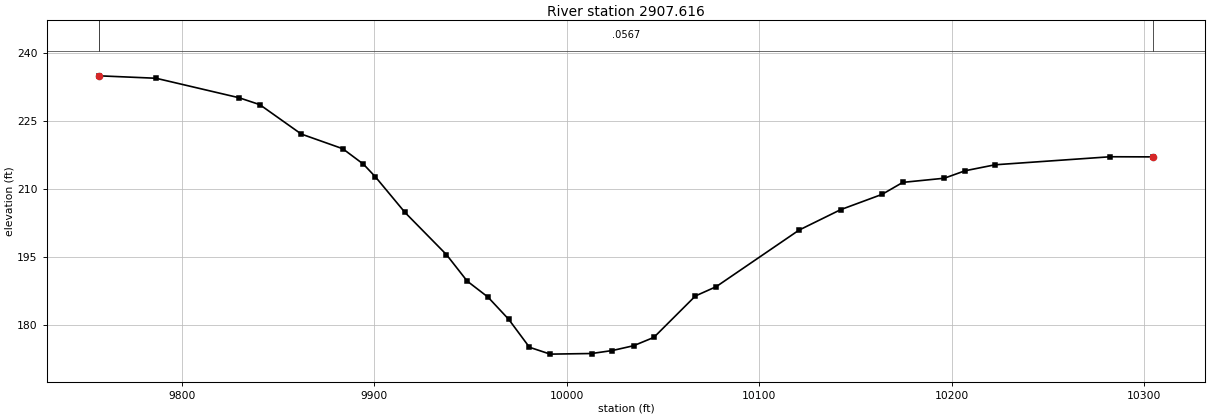
Type RM Length L Ch R = 1 ,2907.616,0.000000,0.000000,0.000000
XS GIS Cut Line= 2
 461841.53364411837337.665109843462045.526699692837845.477609858
#Sta/Elev= 30
9757.193234.94529786.651234.40849829.758230.11169840.535228.58839862.088222.0969
9883.642218.85539894.418215.43489900.628212.63959915.972204.79269937.525195.4797
9948.302189.63499959.078 186.1139969.855181.20569980.632175.03349991.408173.5181
10012.96173.654110023.74174.315110034.76175.376310045.29177.217210066.85186.3537
10077.62188.396610120.73200.900710142.28205.398410163.84 208.78410174.61 211.428
10196.17212.345110206.94 213.98910222.55 215.31110282.38217.083110304.45217.0539
#Mann= 3 , 0 , 0
9757.193  0.0567       09757.193  0.0567       010304.45  0.0567       0
#XS Ineff= 2 , 0
       0                               0
Bank Sta=9757.193,10304.45
Exp/Cntr=0.3,0.1